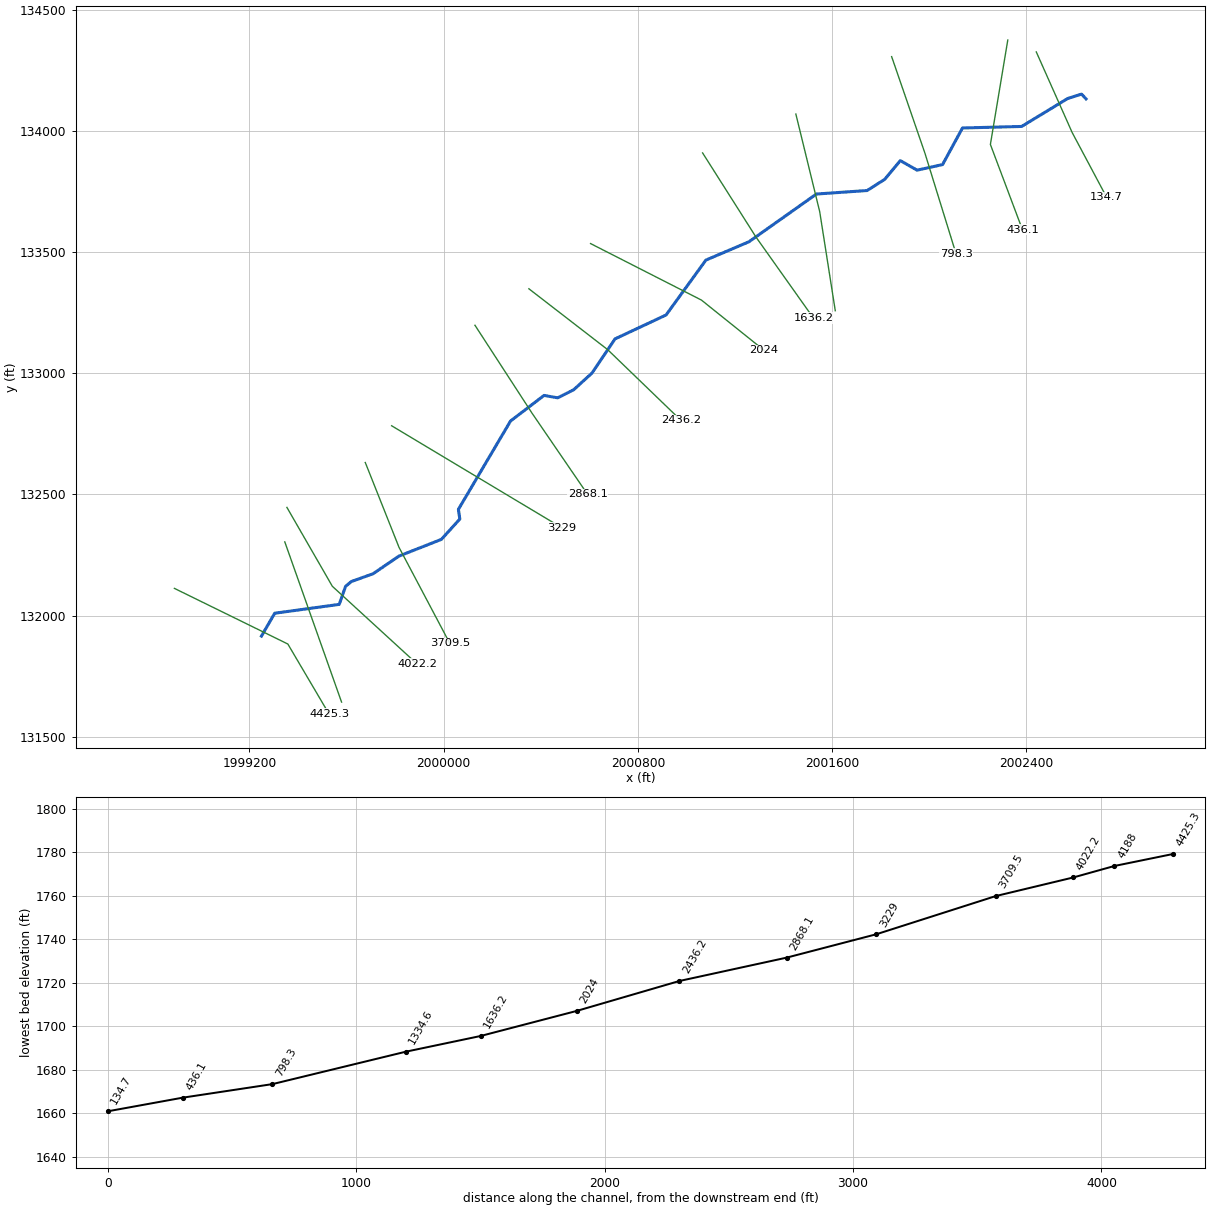
--- WstFkAdRn.prj (project) ---

Proj Title=WstFkAdRn
Current Plan=p01
Default Exp/Contr=0,0
English Units
Geom File=g01
Flow File=f01
Plan File=p01
BEGIN DESCRIPTION:
END DESCRIPTION:
DSS Export Rating Curves= 0
DSS Export Rating Curve Sorted= 0
DSS Export Volume Flow Curves= 0
DXF OffsetX= 0
DXF OffsetY= 0
DXF ScaleX= 0
DXF ScaleY= 0

--- WstFkAdRn.p01 (plan) ---

Plan Title=Floodplain
Program Version=4.00
Geom File=g01
Flow File=f01
K Sum by GR=0
Std Step Tol=0.01
Critical Tol=0.01
Num of Std Step Trials=20
Max Error Tol=0.3
Flow Tol Ratio=0.001
Split Flow NTrial=30
Split Flow Tol=0.02
Split Flow Ratio=0.02
Log Output Level=0
Friction Slope Method=1
Unsteady Friction Slope Method=2
Unsteady Bridges Friction Slope Method=1
Global Log Level=0
CheckData=False
Run HTab=0
Run UNet=0
Run PostProcess=0
UNET Theta=0
UNET Theta Warmup=0
UNET ZTol=0
UNET ZSATol=0
UNET MxIter=0
UNET MaxInSteps=0
UNET DtIC=0
UNET DtMin=0
UNET MaxCRTS=0
UNET WFStab=0
UNET SFStab=0
UNET WFX=0
UNET SFX=0
UNET DSS MLevel=0
UNET DZMax Abort=0
UNET Convert EG Bridges=0
UNET Use Existing IB Tables=0
UNET Froude Limit=0
UNET Froude Power=0
Write IC File=0
Echo Input=False
Echo Output=False
Write Detailed=0

--- WstFkAdRn.f01 (steady flow) ---

Flow Title=NFF Regression Equation
Program Version=4.00
Number of Profiles=1
Profile Names=P100yr
River Rch & RM=WstFkAdRn,Main      ,4425.3
508.8166
River Rch & RM=WstFkAdRn,Main      ,3229
531.5361
River Rch & RM=WstFkAdRn,Main      ,134.7
590.3180
Boundary for River Rch & Prof#=WstFkAdRn,Main      ,1
Up Type=0
Dn Type=3
Dn Slope=0.022056

--- WstFkAdRn.g01 (geometry) ---

Geom Title=USGS 3m DEM
Program Version=4.10

River Reach=WstFkAdRn       ,Main
Reach XY= 30
     1999249.254      131915.743      1999304.03       132009.91
     1999569.655      132046.369     1999595.697      132120.587
     1999619.574      132140.558     1999708.978      132172.671
     1999815.749      132245.588     1999990.469      132314.534
     2000066.423      132398.439     2000060.541      132438.296
     2000275.384      132802.879     2000413.405      132908.348
      2000469.42      132898.445     2000535.296      132931.603
      2000610.78      133000.562     2000705.979      133141.692
     2000916.049      133240.163     2001080.159      133466.656
     2001257.372       133542.15     2001535.281      133739.113
     2001744.373      133753.632      2001816.62      133799.733
     2001881.013      133876.976     2001949.931      133837.583
     2002054.974      133860.581     2002137.033       134011.58
     2002380.704      134017.911     2002570.782      134133.428
     2002627.491      134151.281     2002646.084      134131.633

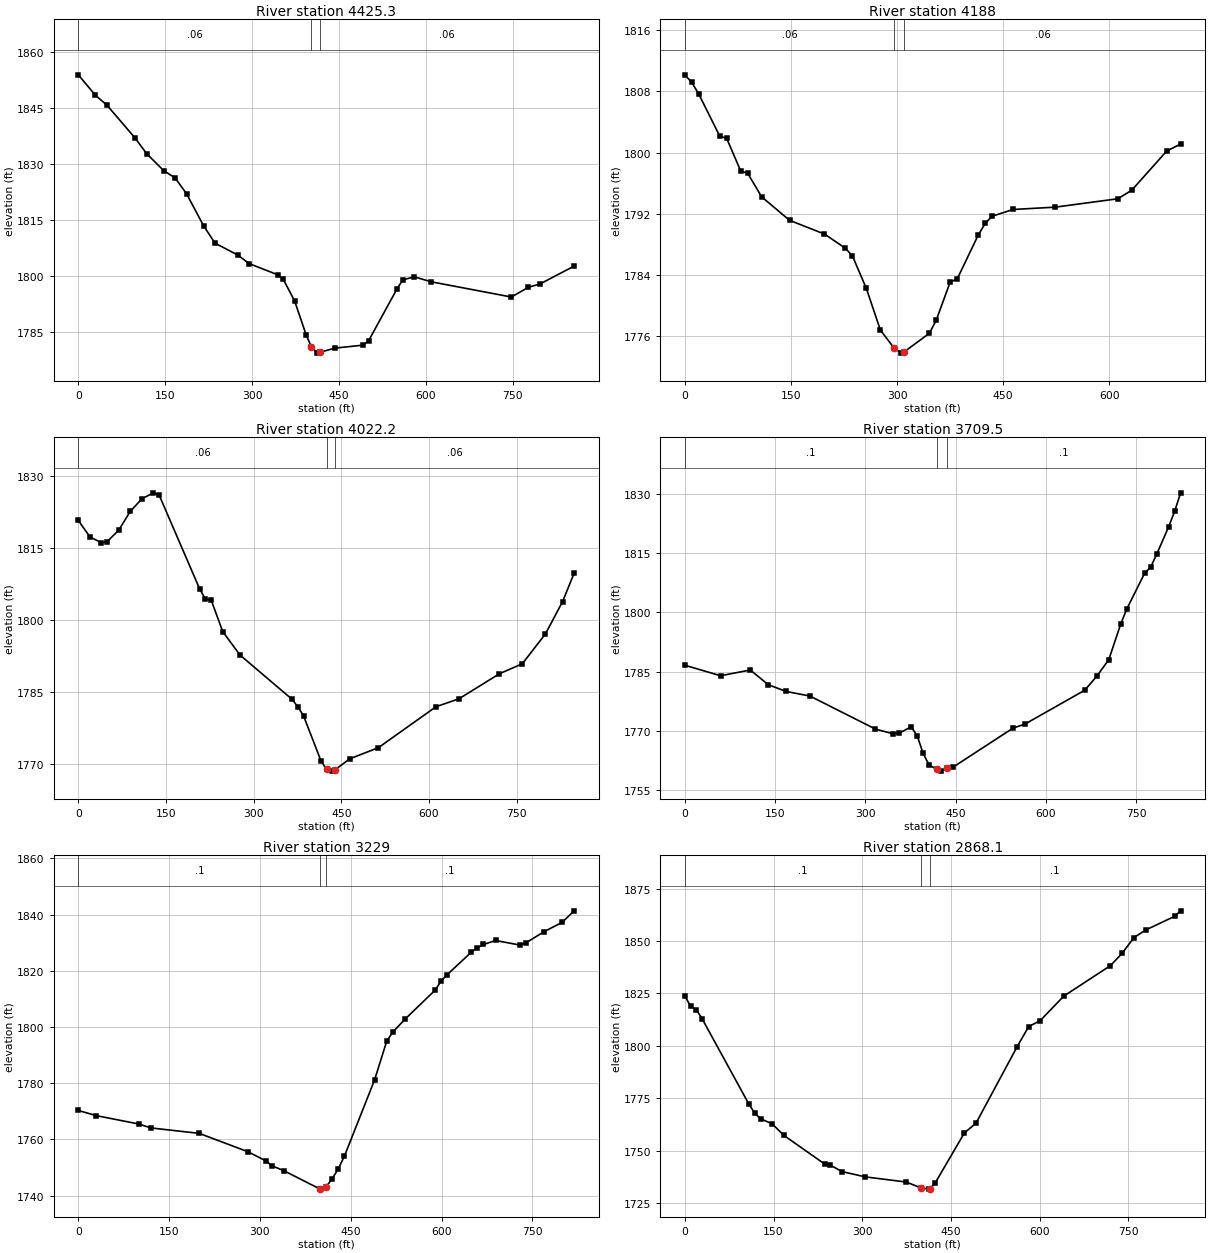
Type RM Length L Ch R = 1 ,4425.3  ,255.1,237.3,219.5
XS GIS Cut Line= 3
     1998890.616      132112.464     1999358.005      131882.856
     1999527.808      131594.155
#Sta/Elev= 30
       0 1853.96    29.5 1848.47    49.1 1845.87    98.2 1836.96   117.9 1832.81
   147.4 1828.26     167 1826.31   186.7 1822.07   216.2 1813.46   235.8 1808.82
   275.1 1805.63   294.8 1803.32   343.9 1800.34   353.7 1799.11   373.4 1793.26
     393 1784.27     402 1781.05   412.7 1779.31     417 1779.52   442.1 1780.64
   491.3 1781.45   501.1 1782.67   550.3 1796.64   560.2 1798.98   579.8 1799.77
   609.4 1798.43   747.3 1794.36   776.9 1796.99   796.6 1797.85   855.7 1802.66
#Mann= 3 , 0 , 0
       0     .06       0     402    .045       0     417     .06       0
Bank Sta=402,417
XS Rating Curve= 0 ,0
Exp/Cntr=0.3,0.1

Type RM Length L Ch R = 1 ,4188    ,154.3,166.1,177.8
XS GIS Cut Line= 2
     1999345.403      132304.319     1999579.238      131643.421
#Sta/Elev= 30
       0 1810.18     9.9 1809.18    19.8 1807.65    49.4 1802.16    59.2 1801.87
      79  1797.6    88.9  1797.3   108.6 1794.22   148.1 1791.14   197.5 1789.34
   227.1 1787.48     237 1786.48   256.7 1782.22   276.5 1776.78   295.6 1774.46
   306.1 1773.76   310.6 1773.96   345.6 1776.34   355.5 1778.07   375.2 1783.07
   385.1 1783.46   414.7 1789.18   424.6 1790.73   434.4 1791.67   464.1 1792.56
   523.3 1792.86   612.2 1793.96   631.9 1795.08   681.3  1800.2     701 1801.12
#Mann= 3 , 0 , 0
       0     .06       0   295.6    .045       0   310.6     .06       0
Bank Sta=295.6,310.6
XS Rating Curve= 0 ,0
Exp/Cntr=0.3,0.1

Type RM Length L Ch R = 1 ,4022.2  ,319.9,312.3,304.8
XS GIS Cut Line= 3
     1999354.185      132446.432     1999541.432      132120.892
     1999889.866      131801.182
#Sta/Elev= 30
       0 1820.78    19.8 1817.35    39.5 1816.11    49.4 1816.36    69.2 1818.77
      89 1822.68   108.7 1825.29   128.5 1826.54   138.4 1826.04   207.5 1806.51
   217.4 1804.37   227.3 1804.16   247.1 1797.57   276.7 1792.68   365.7 1783.45
   375.6 1781.88   385.4 1779.99     415 1770.66   424.7 1768.82   434.7 1768.46
   439.7 1768.77   464.2 1771.02   513.5 1773.36     612  1781.9   651.4 1783.56
   720.4 1788.77   759.8 1790.88   799.2 1797.09   828.7 1803.86   848.4  1809.8
#Mann= 3 , 0 , 0
       0     .06       0   424.7    .045       0   439.7     .06       0
Bank Sta=424.7,439.7
XS Rating Curve= 0 ,0
Exp/Cntr=0.3,0.1

Type RM Length L Ch R = 1 ,3709.5  ,467.6,480.5,493.4
XS GIS Cut Line= 3
     1999677.048      132631.606     1999815.873      132281.916
     2000024.941      131885.991
#Sta/Elev= 30
       0 1786.66    59.4    1784   108.9 1785.45   138.6 1781.74   168.3 1780.03
   207.9 1778.87   316.8 1770.52   346.5 1769.32   356.4  1769.5   376.2 1771.09
   386.2 1768.84   396.1 1764.35   406.1 1761.42   418.3  1760.4     426 1759.89
   435.9 1760.76   445.9  1760.9   545.4 1770.76   565.3 1771.78   664.8 1780.35
   684.7 1783.89   704.6 1788.06   724.5  1797.1   734.4 1800.83   764.3 1809.95
   774.2 1811.44   784.2  1814.7   804.1 1821.65     814 1825.53     824 1830.23
#Mann= 3 , 0 , 0
       0      .1       0   418.3    .045       0   435.9      .1       0
Bank Sta=418.3,435.9
XS Rating Curve= 0 ,0
Exp/Cntr=0.3,0.1

Type RM Length L Ch R = 1 ,3229    ,371.3,361,350.6
XS GIS Cut Line= 3
     1999785.509      132783.212     2000136.651      132572.525
     2000487.794      132361.838
#Sta/Elev= 30
       0 1770.31      30 1768.46    99.9  1765.5   119.8  1764.1   199.8 1762.16
   279.7 1755.66   309.6 1752.41   319.6 1750.65   339.6 1748.87   399.5 1742.32
   409.5 1743.24   419.5 1746.03   429.5 1749.65   439.5 1754.04   489.4 1781.22
   509.4    1795   519.4  1798.2   539.3 1802.74   589.3 1813.13   599.3 1816.41
   609.3 1818.67   649.2 1826.66   659.2 1828.21   669.2 1829.39   689.2 1830.81
   729.1  1829.2   739.1 1829.93   769.1 1833.93     799 1837.24     819 1841.37
#Mann= 3 , 0 , 0
       0      .1       0   399.5    .045       0   409.5      .1       0
Bank Sta=399.5,409.5
XS Rating Curve= 0 ,0
Exp/Cntr=0.3,0.1

Type RM Length L Ch R = 1 ,2868.1  ,424.5,431.6,436
XS GIS Cut Line= 3
     2000128.786      133197.817     2000364.404      132834.385
     2000593.035      132499.875
#Sta/Elev= 30
       0 1823.94     9.8 1818.81    19.7 1817.16    29.5  1812.8   108.3 1772.18
   118.1 1767.86     128 1765.17   147.7 1762.75   167.3 1757.26   236.2  1743.6
   246.1    1743   265.8 1739.94   305.2  1737.4   374.1 1734.96   399.2 1732.18
   413.4 1731.56   414.2  1731.8   423.3  1734.5   472.7 1758.38   492.4 1763.08
   561.6 1799.42   581.4 1809.17   601.1 1812.07   640.7 1823.72   719.7  1838.3
   739.5 1844.18   759.2 1851.65     779 1855.25   828.4 1861.87   838.3 1864.45
#Mann= 3 , 0 , 0
       0      .1       0   399.2    .045       0   414.2      .1       0
Bank Sta=399.2,414.2
XS Rating Curve= 0 ,0
Exp/Cntr=0.3,0.1

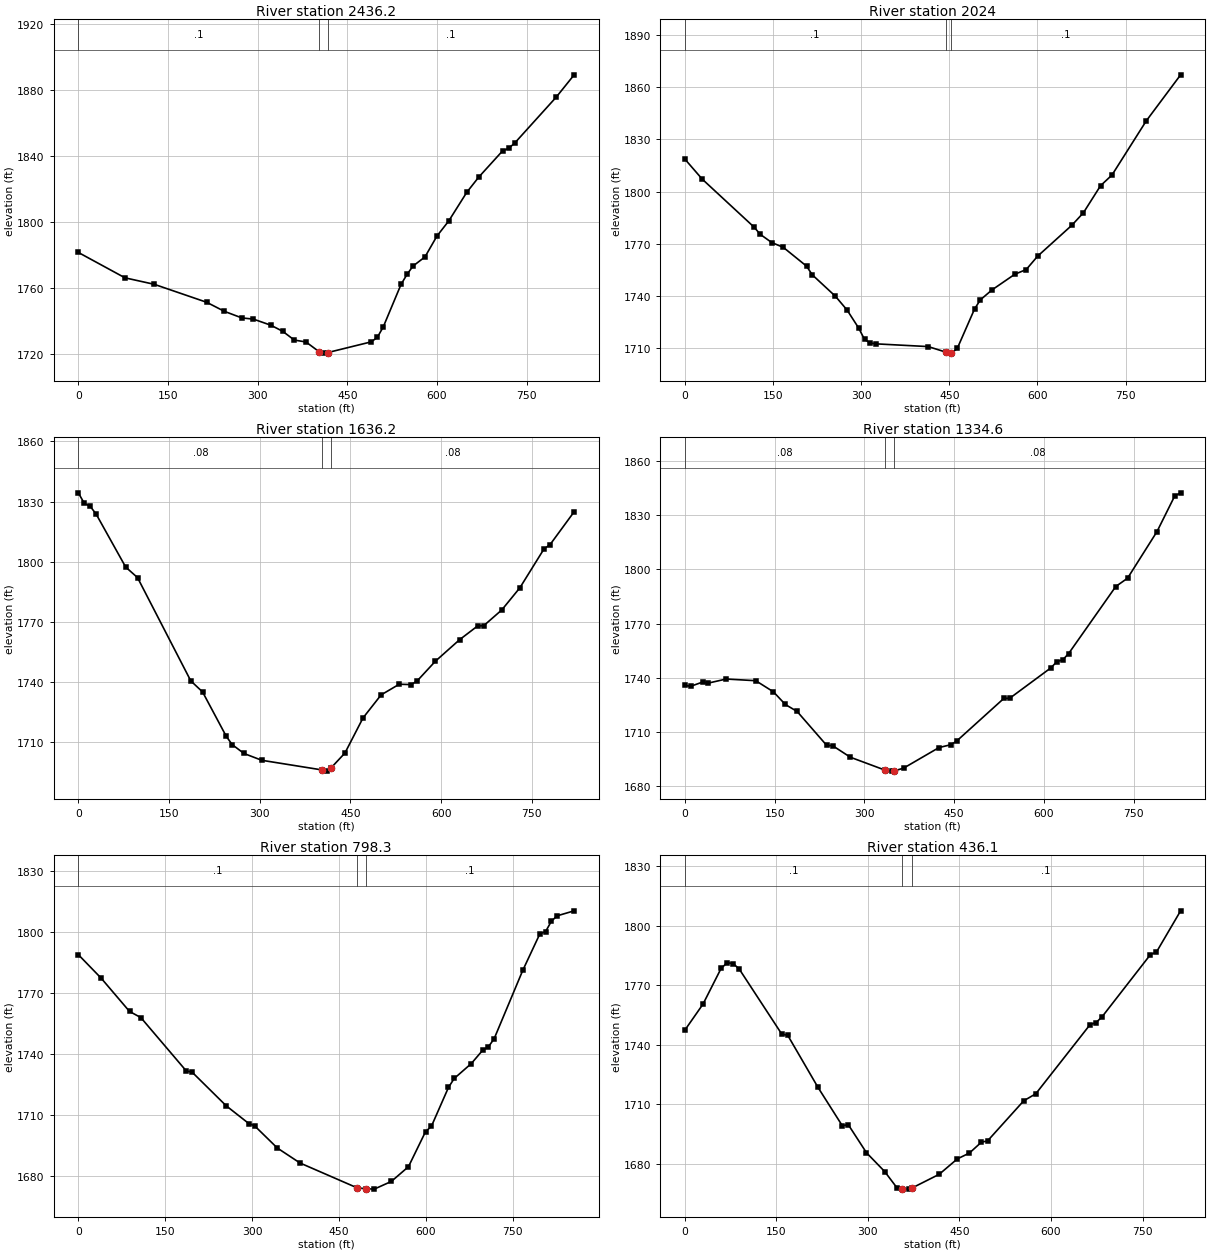
Type RM Length L Ch R = 1 ,2436.2  ,407.9,412.1,418.9
XS GIS Cut Line= 3
     2000351.066      133348.229     2000675.521      133097.186
     2000977.085       132805.73
#Sta/Elev= 30
       0 1781.76    78.1 1766.39     127 1762.47   214.9 1751.57   244.2 1746.13
   273.5 1742.13     293 1741.39   322.3 1737.68   341.9 1734.03   361.4 1728.71
   380.9 1727.57   402.7 1721.71   410.2 1720.81   417.7 1721.19   490.1 1727.64
   500.1 1730.28   510.1  1736.6     540 1762.45     550 1768.49     560 1773.53
     580 1779.05     600 1791.66   619.9  1800.9   649.9 1818.14   669.9 1827.34
   709.8 1843.22   719.8 1844.76   729.8 1847.85   799.7 1875.82   829.6 1889.28
#Mann= 3 , 0 , 0
       0      .1       0   402.7    .045       0   417.7      .1       0
Bank Sta=402.7,417.7
XS Rating Curve= 0 ,0
Exp/Cntr=0.3,0.1

Type RM Length L Ch R = 1 ,2024    ,400,388,377
XS GIS Cut Line= 3
      2000604.89      133534.839     2001061.708      133301.705
     2001319.653      133094.548
#Sta/Elev= 30
       0  1818.7    29.6 1807.15   118.4 1779.37   128.2 1775.43   147.9 1770.68
   167.7 1767.88   207.1 1757.11     217 1752.08   256.4 1739.74   276.2 1731.82
   295.9 1721.47   305.8 1714.98   315.6 1712.89   325.5  1712.4   414.2 1710.83
   443.8 1707.69   453.7 1707.07   463.6 1709.74   493.1  1732.5     503 1737.74
   522.6 1743.39   561.5 1752.42     581 1755.15   600.4 1762.83   658.8 1780.67
   678.3  1787.8   707.5 1803.38   726.9 1809.49   785.3 1840.67   843.7 1867.12
#Mann= 3 , 0 , 0
       0      .1       0   443.8    .045       0   453.7      .1       0
Bank Sta=443.8,453.7
XS Rating Curve= 0 ,0
Exp/Cntr=0.3,0.1

Type RM Length L Ch R = 1 ,1636.2  ,309.1,301.4,292.7
XS GIS Cut Line= 3
     2001066.472      133908.779     2001286.449      133561.538
     2001522.899       133227.74
#Sta/Elev= 30
       0 1834.36     9.8 1829.14    19.6 1827.63    29.4 1823.78    78.3 1797.32
    97.9 1792.06     186 1740.53   205.5 1735.01   244.7 1712.85   254.5 1708.73
     274  1704.3   303.4 1700.91   403.6 1696.07   411.1  1695.5   418.6 1697.31
     441 1704.55   470.9 1722.06   500.8 1733.54   530.8 1738.86   550.7 1738.67
   560.7  1740.6   590.6 1750.35   630.6 1761.08   660.5 1767.95   670.5 1768.06
   700.4 1775.93   730.3 1786.97   770.2 1806.36   780.2  1808.5   820.1 1824.92
#Mann= 3 , 0 , 0
       0     .08       0   403.6    .045       0   418.6     .08       0
Bank Sta=403.6,418.6
XS Rating Curve= 0 ,0
Exp/Cntr=0.3,0.1

Type RM Length L Ch R = 1 ,1334.6  ,534.8,536.2,536.6
XS GIS Cut Line= 3
     2001450.688      134069.068      2001548.98      133666.109
      2001613.03      133257.788
#Sta/Elev= 30
       0 1735.74     9.9 1735.26    29.6 1737.58    39.5 1737.04    69.1 1739.28
   118.5 1738.35   148.1 1732.17   167.9 1725.17   187.6 1721.31     237 1702.51
   246.9 1702.35   276.5 1695.96   334.6 1688.79   345.6 1688.26   349.6 1688.37
   365.4 1689.91   424.6 1701.32   444.3 1702.89   454.1 1704.93   532.9 1728.55
   542.7 1728.63   611.6 1745.51   621.4 1748.92   631.3 1749.93   641.1 1753.41
   719.8 1790.53   739.5 1795.14   788.7 1820.99   818.2 1840.66   828.1 1842.42
#Mann= 3 , 0 , 0
       0     .08       0   334.6    .045       0   349.6     .08       0
Bank Sta=334.6,349.6
XS Rating Curve= 0 ,0
Exp/Cntr=0.3,0.1

Type RM Length L Ch R = 1 ,798.3   ,372.6,361.7,350.8
XS GIS Cut Line= 3
     2001845.252       134305.92     2001982.695      133906.594
     2002110.814      133491.783
#Sta/Elev= 30
       0 1788.93    39.3 1777.38    88.4 1760.95     108 1757.91   186.6 1731.56
   196.4 1731.06   255.4 1714.44   294.6 1705.66   304.5 1704.56   343.8 1693.61
     383 1686.23   481.8 1673.97   496.8 1673.57   511.1 1673.36   540.7 1677.15
   570.3 1684.43   599.9 1701.76   609.8 1704.26   639.4 1723.49   649.3  1727.9
   678.9 1735.27   698.6 1741.85   708.5 1743.54   718.3  1747.5   767.7 1781.17
   797.3 1799.21   807.1 1800.28     817 1805.32   826.9 1808.05   856.5 1810.53
#Mann= 3 , 0 , 0
       0      .1       0   481.8    .045       0   496.8      .1       0
Bank Sta=481.8,496.8
XS Rating Curve= 0 ,0
Exp/Cntr=0.3,0.1

Type RM Length L Ch R = 1 ,436.1   ,288.2,301.4,314.6
XS GIS Cut Line= 3
     2002323.668      134374.375     2002252.029      133943.647
     2002384.057      133591.889
#Sta/Elev= 30
       0 1747.21    29.8 1760.36    59.5 1778.39    69.5 1781.26    79.4  1780.8
    89.3    1778   158.8  1745.3   168.7 1744.62   218.3 1718.36     258  1699.1
   267.9 1699.58   297.7 1685.45   327.5 1675.98   347.3 1667.91   356.6 1667.18
   367.2 1667.11   371.6 1667.57   416.8 1674.58   446.5 1682.34   466.3  1685.3
   486.1 1690.81     496  1691.4   555.3 1711.63   575.1 1715.18     664 1750.02
   673.9 1751.08   683.8 1754.03   762.9 1785.32   772.8 1786.62   812.4  1807.4
#Mann= 3 , 0 , 0
       0      .1       0   356.6    .045       0   371.6      .1       0
Bank Sta=356.6,371.6
XS Rating Curve= 0 ,0
Exp/Cntr=0.3,0.1

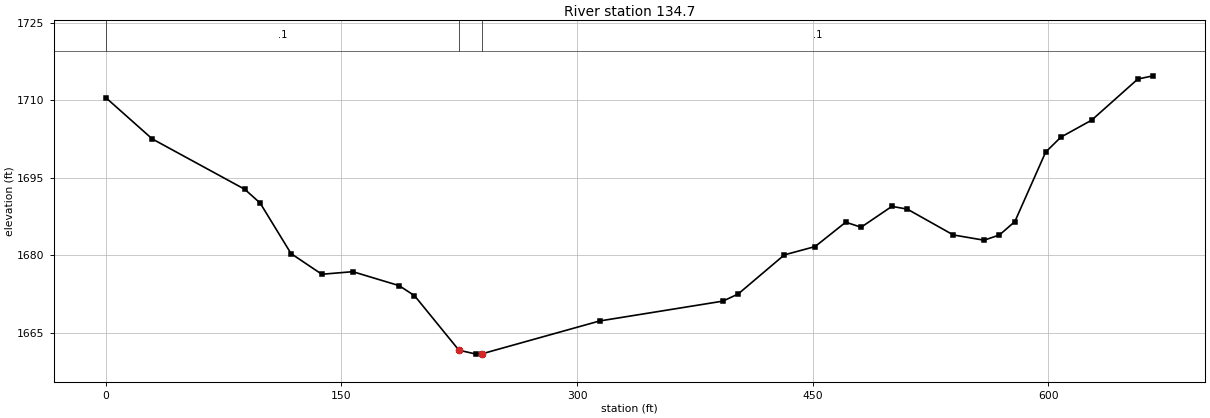
Type RM Length L Ch R = 1 ,134.7   ,188.1,134.7,144.8
XS GIS Cut Line= 3
     2002441.058      134325.334     2002588.692      133993.158
     2002731.122      133725.334
#Sta/Elev= 30
       0 1710.47    29.5  1702.5    88.4 1692.75    98.2 1690.09   117.9  1680.3
   137.5  1676.3   157.2  1676.8   186.7  1674.1   196.5 1672.16   224.8  1661.6
   235.8 1660.84   239.8 1660.93   314.4 1667.26   392.9  1671.1   402.6 1672.48
     432 1680.05   451.6 1681.66   471.1 1686.38   480.9  1685.4   500.5 1689.44
   510.3 1688.91   539.6 1683.91   559.2 1682.89     569 1683.91   578.8  1686.5
   598.4 1699.94   608.1 1702.84   627.7 1706.13   657.1 1714.09   666.8 1714.71
#Mann= 3 , 0 , 0
       0      .1       0   224.8    .045       0   239.8      .1       0
Bank Sta=224.8,239.8
XS Rating Curve= 0 ,0
Exp/Cntr=0.3,0.1

Chan Stop Cuts=-1
Use User Specified Reach Order=0
Composite Channel Slope=5